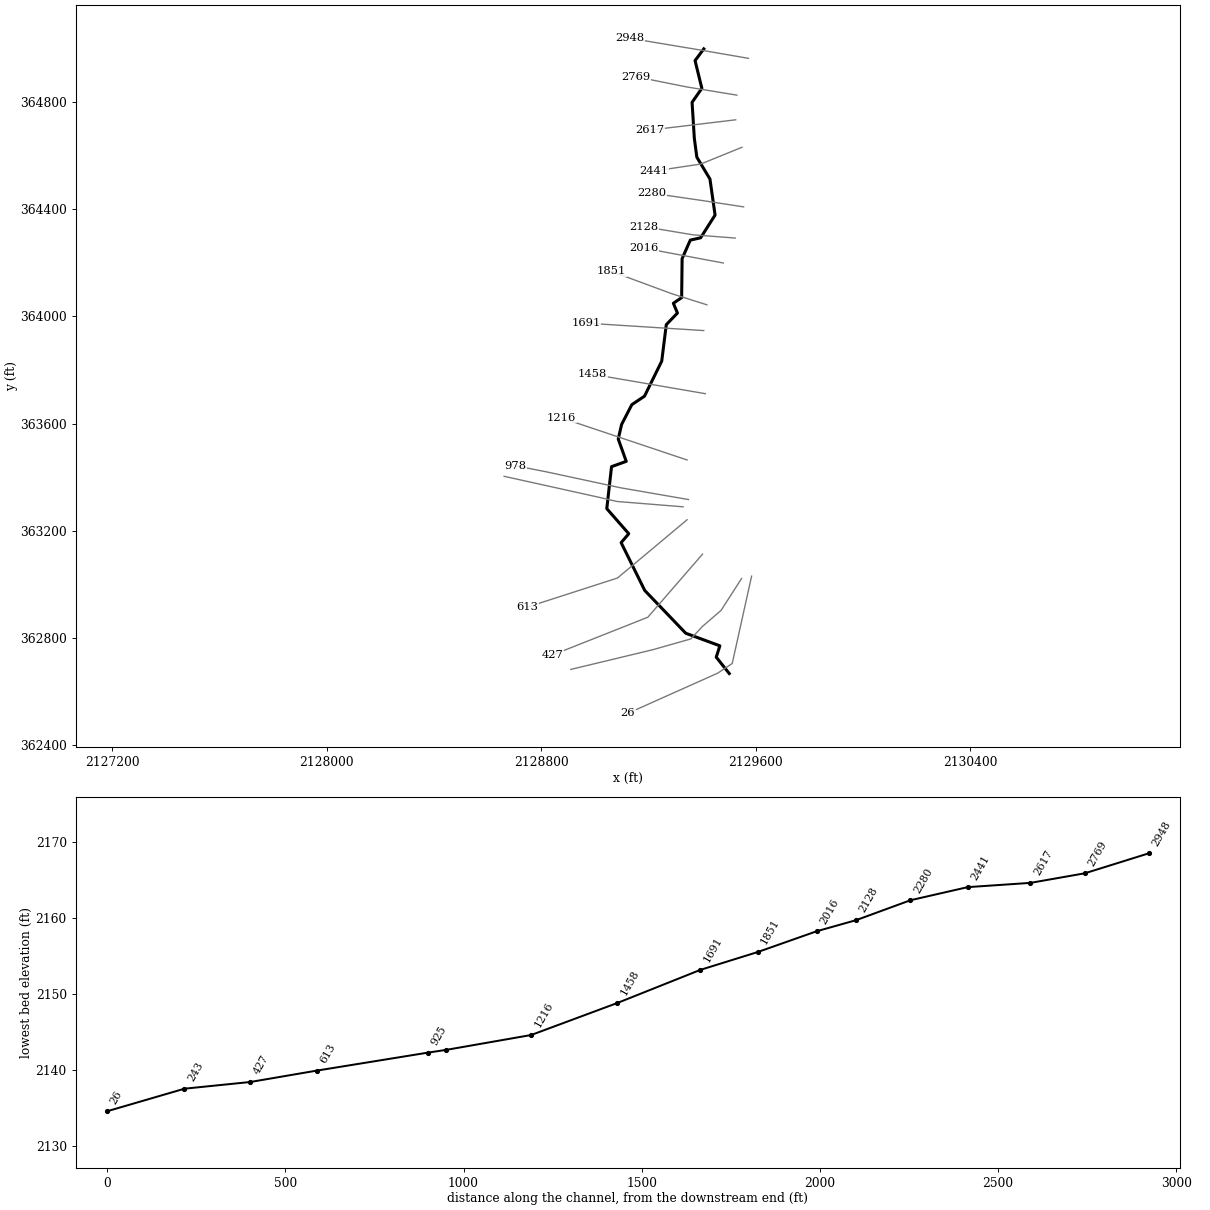
--- CLBRSNCKT1.prj (project) ---

Proj Title=CLBRSNCKT1
Current Plan=p01
Default Exp/Contr=0.3,0.1
English Units
Geom File=g01
Flow File=f01
Plan File=p01
Y Axis Title=Elevation
X Axis Title(PF)=Main Channel Distance
X Axis Title(XS)=Station
BEGIN DESCRIPTION:
Stream Name- Culberson Creek Tributary 1
Flood Zone: Zone A
Greenbrier County, WV
County-Wide Study
WVDHSEM-2018-3, Flood Risk Project
HEC-RAS Version: 5.0.7
General Notes:
For the Hydrology regression was used.
END DESCRIPTION:
DSS Export Rating Curves= 0
DSS Export Rating Curve Sorted= 0
DSS Export Volume Flow Curves= 0
DXF Filename=CLBRSNCKT1.G2.
DXF OffsetX= 0
DXF OffsetY= 0
DXF ScaleX= 1
DXF ScaleY= 10

--- CLBRSNCKT1.p01 (plan) ---

Plan Title=Floodplain
Program Version=5.07
Short Identifier=Floodplain
Geom File=g01
Flow File=f01
Subcritical Flow
K Sum by GR= 0
Std Step Tol= 0.01
Critical Tol= 0.01
Num of Std Step Trials= 20
Max Error Tol= 0.3
Flow Tol Ratio= 0.001
Split Flow NTrial= 30
Split Flow Tol= 0.02
Split Flow Ratio= 0.02
Log Output Level= 0
Friction Slope Method= 1
Unsteady Friction Slope Method= 2
Unsteady Bridges Friction Slope Method= 1
Parabolic Critical Depth
Global Vel Dist= 0 , 0 , 0
Global Log Level= 0
CheckData=True
Encroach Param=-1 ,0,0, 0
Computation Interval=1MIN
Output Interval=1HOUR
Instantaneous Interval=1HOUR
Mapping Interval=1HOUR
Computation Time Step Use Courant=        0
Computation Time Step Use Time Series=    0
Computation Time Step Count To Double=0
Computation Time Step Max Doubling=0
Computation Time Step Max Halving=0
Computation Time Step Residence Courant=0
Run HTab= 0
Run UNet= 0
Run Sediment= 0
Run PostProcess= 0
Run WQNet= 0
Run RASMapper= 0
UNET Theta= 1
UNET Theta Warmup= 1
UNET ZTol= 0.02
UNET ZSATol= 0.02
UNET MxIter= 20
UNET Max Iter WO Improvement= 0
UNET MaxInSteps= 0
UNET DtIC= 0
UNET DtMin= 0
UNET MaxCRTS= 20
UNET WFStab= 2
UNET SFStab= 1
UNET WFX= 1
UNET SFX= 1
UNET 1D Methodology=Finite Difference
UNET DSS MLevel= 4
UNET Pardiso=0
UNET DZMax Abort= 100
UNET Use Existing IB Tables=-1
UNET Froude Reduction=False
UNET Froude Limit= 0.8
UNET Froude Power= 4
UNET D1 Cores= 0
UNET D2 Coriolis=0
UNET D2 Cores= 0
UNET D2 Theta= 1
UNET D2 Theta Warmup= 1
UNET D2 Z Tol= 0.01
UNET D2 Volume Tol= 0.01
UNET D2 Max Iterations= 20
UNET D2 Equation= 0
UNET D2 RampUpFraction=0.1
UNET D2 TimeSlices= 1
UNET D2 BCVolumeCheck=0
UNET D1D2 MaxIter= 0
UNET D1D2 ZTol=0.01
UNET D1D2 QTol=0.1
UNET D1D2 MinQTol=1
Write IC File= 0
Write IC File at Fixed DateTime=0
Write IC File at Sim End=0
Echo Input=False
Echo Parameters=False
Echo Output=False
Write Detailed= 0
HDF Write Warmup=0
HDF Write Time Slices=0
HDF Flush=0
HDF Face Node Velocities=0
HDF Compression= 1
HDF Chunk Size= 1
HDF Spatial Parts= 1
HDF Use Max Rows=0
HDF Fixed Rows= 1
Calibration Method= 0
Calibration Iterations= 20
Calibration Max Change=0.05
Calibration Tolerance=0.2
Calibration Maximum=1.5
Calibration Minimum=0.5
Calibration Optimization Method= 1
WQ AD Non Conservative
WQ ULTIMATE=-1
WQ Max Comp Step=1HOUR
WQ Output Interval=15MIN
WQ Output Selected Increments= 0
WQ Output face flow=0
WQ Output face velocity=0
WQ Output face area=0
WQ Output face dispersion=0
WQ Output cell volume=0
WQ Output cell surface area=0
WQ Output cell continuity=0
WQ Output cumulative cell continuity=0
WQ Output face conc=0
WQ Output face dconc_dx=0
WQ Output face courant=0
WQ Output face peclet=0
WQ Output face adv mass=0
WQ Output face disp mass=0
WQ Output cell mass=0
WQ Output cell source sink temp=0
WQ Output nsm pathways=0
WQ Output nsm derived pathways=0
WQ Output MaxMinRange=-1
WQ Daily Max Min Mean=-1
WQ Daily Range=0
WQ Daily Time=0
WQ Create Restart=0
WQ Fixed Restart=0
WQ System Summary=0
WQ Write To DSS=0
WQ Use Fixed Temperature=0
Sorting and Armoring Iterations= 10
XS Update Threshold= 0.02
Bed Roughness Predictor= 0
Hydraulics Update Threshold= 0.02
Energy Slope Method= 1
Volume Change Method= 1
Sediment Retention Method= 0
XS Weighting Method= 0
Number of US Weighted Cross Sections= 1
Number of DS Weighted Cross Sections= 1
Upstream XS Weight=0
Main XS Weight=1
Downstream XS Weight=0
Number of DS XS's Weighted with US Boundary= 1
Upstream Boundary Weight= 1
Weight of XSs Associated with US Boundary= 0
Number of US XS's Weighted with DS Boundary= 1
Downstream Boundary Weight= 0.5
Weight of XSs Associated with DS Boundary= 0.5
Percentile Method= 0
Sediment Output Level= 3
Mass or Volume Output= 0
Output Increment Type= 1
Profile and TS Output Increment= 1
XS Output Flag= 0
XS Output Increment= 10
Write Gradation File= 0
Read Gradation Hotstart= 0
Write HDF5 File= 1
Write Binary Output= 1
Write DSS Sediment File= 0
SV Curve= 0
Specific Gage Flag= 0

--- CLBRSNCKT1.f01 (steady flow) ---

Flow Title=Flow
Program Version=5.07
Number of Profiles= 6
Profile Names=f1p,f10p,f4p,f2p,f02p,f1pplus
River Rch & RM=BURNSRN,Main            ,9203
     572     302     402     484     799     846
River Rch & RM=BURNSRN,Main            ,7195
     649     345     457     550     905     960
River Rch & RM=BURNSRN,Main            ,4526
    1220     661     867    1040    1670    1800
River Rch & RM=BURNSRNT1,Main            ,2875
     504     265     353     426     705     745
River Rch & RM=BURNSRNT1,Main            ,2198
     669     356     472     568     932     990
River Rch & RM=CLBRSNCKT1,Main            ,2948
     116    57.4    78.7    96.5     166     171
River Rch & RM=CLBRSNCKT1,Main            ,2280
     138    69.1    94.4     116     198     210
River Rch & RM=CLBRSNCKT1,Main            ,1216
     156    78.2     107     130     223     230
River Rch & RM=CLBRSNCKT1,Main            ,243
     178    89.6     122     149     253     300
River Rch & RM=CLBRSNCKT2,Main            ,5369
     223     114     154     187     317     330
River Rch & RM=CLBRSNCKT2,Main            ,3799
     483     253     338     408     676     714
River Rch & RM=INDIANCK,Main            ,11519
     313     162     218     264     443     463
River Rch & RM=INDIANCK,Main            ,9807
     520     274     365     440     728     769
River Rch & RM=INDIANCK,Main            ,8108
     581     307     409     492     812     860
River Rch & RM=INDIANCK,Main            ,6227
     647     344     456     549     902     958
River Rch & RM=LTROARCK,Main            ,4000
     648     344     456     549     903     958
River Rch & RM=MLGNCKTR5,Main            ,7678
     581     307     409     492     812     860
River Rch & RM=MLGNCKTR5,Main            ,5118
     654     347     461     554     911     967
River Rch & RM=MLGNCKTR5,Main            ,2636
     728     388     514     617    1010    1080
River Rch & RM=ROARINGCK,Main            ,17918
     544     287     382     461     761     805
River Rch & RM=ROARINGCK,Main            ,16996
     613     325     431     519     855     906
River Rch & RM=ROARINGCK,Main            ,14906
     713     380     504     605     992    1060
River Rch & RM=ROARINGCK,Main            ,11661
     864     464     612     734    1200    1280
River Rch & RM=ROARINGCK,Main            ,8657
     964     520     685     820    1330    1430
River Rch & RM=ROARINGCK,Main            ,4987
    1570     861    1120    1340    2150    2320
Boundary for River Rch & Prof#=BURNSRN,Main            , 1
Up Type= 0
Dn Type= 3
Dn Slope=0.0012
Boundary for River Rch & Prof#=BURNSRN,Main            , 2
Up Type= 0
Dn Type= 3
Dn Slope=0.0012
Boundary for River Rch & Prof#=BURNSRN,Main            , 3
Up Type= 0
Dn Type= 3
Dn Slope=0.0012
Boundary for River Rch & Prof#=BURNSRN,Main            , 4
Up Type= 0
Dn Type= 3
Dn Slope=0.0012
Boundary for River Rch & Prof#=BURNSRN,Main            , 5
Up Type= 0
Dn Type= 3
Dn Slope=0.0012
Boundary for River Rch & Prof#=BURNSRN,Main            , 6
Up Type= 0
Dn Type= 3
Dn Slope=0.0012
Boundary for River Rch & Prof#=BURNSRNT1,Main            , 1
Up Type= 0
Dn Type= 3
Dn Slope=0.00496
Boundary for River Rch & Prof#=BURNSRNT1,Main            , 2
Up Type= 0
Dn Type= 3
Dn Slope=0.00496
Boundary for River Rch & Prof#=BURNSRNT1,Main            , 3
Up Type= 0
Dn Type= 3
Dn Slope=0.00496
Boundary for River Rch & Prof#=BURNSRNT1,Main            , 4
Up Type= 0
Dn Type= 3
Dn Slope=0.00496
Boundary for River Rch & Prof#=BURNSRNT1,Main            , 5
Up Type= 0
Dn Type= 3
Dn Slope=0.00496
Boundary for River Rch & Prof#=BURNSRNT1,Main            , 6
Up Type= 0
Dn Type= 3
Dn Slope=0.00496
Boundary for River Rch & Prof#=CLBRSNCKT1,Main            , 1
Up Type= 0
Dn Type= 3
Dn Slope=0.00848
Boundary for River Rch & Prof#=CLBRSNCKT1,Main            , 2
Up Type= 0
Dn Type= 3
Dn Slope=0.00848
Boundary for River Rch & Prof#=CLBRSNCKT1,Main            , 3
Up Type= 0
Dn Type= 3
Dn Slope=0.00848
Boundary for River Rch & Prof#=CLBRSNCKT1,Main            , 4
Up Type= 0
Dn Type= 3
Dn Slope=0.00848
Boundary for River Rch & Prof#=CLBRSNCKT1,Main            , 5
Up Type= 0
Dn Type= 3
Dn Slope=0.00848
Boundary for River Rch & Prof#=CLBRSNCKT1,Main            , 6
Up Type= 0
Dn Type= 3
Dn Slope=0.00848
Boundary for River Rch & Prof#=CLBRSNCKT2,Main            , 1
Up Type= 0
Dn Type= 3
Dn Slope=0.00274
Boundary for River Rch & Prof#=CLBRSNCKT2,Main            , 2
Up Type= 0
Dn Type= 3
Dn Slope=0.00274
Boundary for River Rch & Prof#=CLBRSNCKT2,Main            , 3
Up Type= 0
Dn Type= 3
Dn Slope=0.00274
Boundary for River Rch & Prof#=CLBRSNCKT2,Main            , 4
Up Type= 0
Dn Type= 3
Dn Slope=0.00274
Boundary for River Rch & Prof#=CLBRSNCKT2,Main            , 5
Up Type= 0
Dn Type= 3
Dn Slope=0.00274
Boundary for River Rch & Prof#=CLBRSNCKT2,Main            , 6
Up Type= 0
Dn Type= 3
Dn Slope=0.00274
Boundary for River Rch & Prof#=INDIANCK,Main            , 1
Up Type= 0
Dn Type= 3
Dn Slope=0.00176
Boundary for River Rch & Prof#=INDIANCK,Main            , 2
Up Type= 0
Dn Type= 3
Dn Slope=0.00176
Boundary for River Rch & Prof#=INDIANCK,Main            , 3
Up Type= 0
Dn Type= 3
Dn Slope=0.00176
Boundary for River Rch & Prof#=INDIANCK,Main            , 4
Up Type= 0
Dn Type= 3
Dn Slope=0.00176
Boundary for River Rch & Prof#=INDIANCK,Main            , 5
Up Type= 0
Dn Type= 3
Dn Slope=0.00176
Boundary for River Rch & Prof#=INDIANCK,Main            , 6
Up Type= 0
Dn Type= 3
Dn Slope=0.00176
Boundary for River Rch & Prof#=LTROARCK,Main            , 1
Up Type= 0
Dn Type= 3
Dn Slope=0.04436
Boundary for River Rch & Prof#=LTROARCK,Main            , 2
Up Type= 0
Dn Type= 3
Dn Slope=0.04436
Boundary for River Rch & Prof#=LTROARCK,Main            , 3
Up Type= 0
Dn Type= 3
Dn Slope=0.04436
Boundary for River Rch & Prof#=LTROARCK,Main            , 4
Up Type= 0
Dn Type= 3
Dn Slope=0.04436
Boundary for River Rch & Prof#=LTROARCK,Main            , 5
Up Type= 0
Dn Type= 3
Dn Slope=0.04436
Boundary for River Rch & Prof#=LTROARCK,Main            , 6
Up Type= 0
Dn Type= 3
Dn Slope=0.04436
Boundary for River Rch & Prof#=MLGNCKTR5,Main            , 1
Up Type= 0
Dn Type= 3
Dn Slope=0.0247
Boundary for River Rch & Prof#=MLGNCKTR5,Main            , 2
Up Type= 0
Dn Type= 3
Dn Slope=0.0247
Boundary for River Rch & Prof#=MLGNCKTR5,Main            , 3
Up Type= 0
Dn Type= 3
Dn Slope=0.0247
Boundary for River Rch & Prof#=MLGNCKTR5,Main            , 4
Up Type= 0
Dn Type= 3
Dn Slope=0.0247
Boundary for River Rch & Prof#=MLGNCKTR5,Main            , 5
Up Type= 0
Dn Type= 3
Dn Slope=0.0247
Boundary for River Rch & Prof#=MLGNCKTR5,Main            , 6
Up Type= 0
Dn Type= 3
Dn Slope=0.0247
Boundary for River Rch & Prof#=ROARINGCK,Main            , 1
Up Type= 0
Dn Type= 3
Dn Slope=0.01435
Boundary for River Rch & Prof#=ROARINGCK,Main            , 2
Up Type= 0
Dn Type= 3
Dn Slope=0.01435
Boundary for River Rch & Prof#=ROARINGCK,Main            , 3
Up Type= 0
Dn Type= 3
Dn Slope=0.01435
Boundary for River Rch & Prof#=ROARINGCK,Main            , 4
Up Type= 0
Dn Type= 3
Dn Slope=0.01435
Boundary for River Rch & Prof#=ROARINGCK,Main            , 5
Up Type= 0
Dn Type= 3
Dn Slope=0.01435
Boundary for River Rch & Prof#=ROARINGCK,Main            , 6
Up Type= 0
Dn Type= 3
Dn Slope=0.01435
DSS Import GetInterval= 0
DSS Import GetPeak= 0
DSS Import FillOption= 0

--- CLBRSNCKT1.g01 (geometry) ---

Geom Title=Geometry
Program Version=5.07

River Reach=CLBRSNCKT1      ,Main
Reach XY= 30
2129406.55452454364997.4665502762129373.91548222364953.716309696
2129399.26287246364850.2440757012129362.80461204364798.160846531
2129371.13792869364664.4803396172129380.51290995 364593.64681986
2129429.47114536364512.0498701932129448.56822005364377.674810871
2129394.74877387364292.9525393692129356.20718428364284.272110537
 2129325.6517992364215.1748077872129323.91558221364069.688550204
2129293.01275688364048.8552585392129308.29061347364012.396998122
2129266.62403011363968.9941977862129249.60995653363832.882921442
2129185.37386453363702.3274082842129138.15184614363670.730358616
 2129099.9573687363596.7718451172129087.45739371363542.605286777
2129117.31822637363459.2721201182129062.45711562363439.480164945
2129044.74881771363282.8830371952129126.69320762 363189.48033686
2129098.22115171363156.1470701992129186.41552913 362977.67465812
 2129339.1934388362818.2996487772129466.45040214362771.424742535
2129452.90876254362729.063606784 2129501.4349122362668.106379613

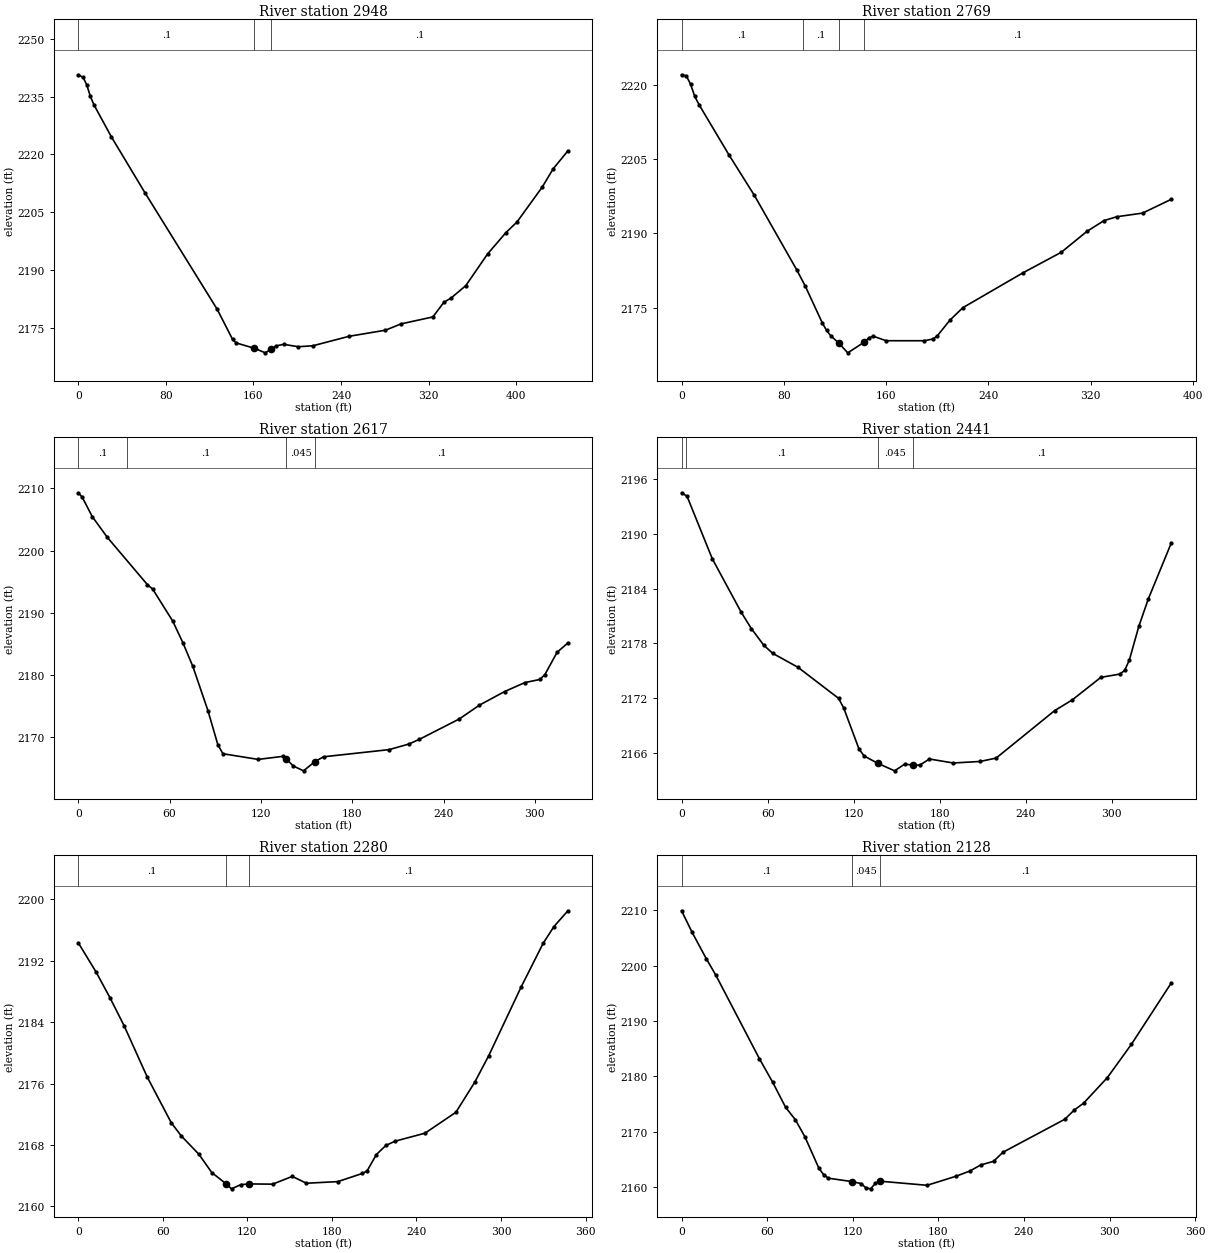
Type RM Length L Ch R = 1 ,2948    ,168,178.7,171.3
XS GIS Cut Line= 3
2129573.21790513364962.0719360262129396.09883678364992.707045361
2129132.24568996365036.725001946
#Sta/Elev= 30
       0 2240.67     4.5 2239.97     7.8 2238.06    11.1 2235.05    14.4 2232.85
    30.3 2224.54    61.1 2209.96   126.9 2179.77     141 2171.93   144.3 2171.02
  160.962169.624   170.9 2168.45  176.482169.477   180.9 2170.27   187.6 2170.66
   200.9 2170.04   214.2 2170.28   247.4 2172.75   280.6 2174.33   294.8 2175.97
   323.9 2177.78   333.9 2181.57   340.6 2182.71   353.9 2185.89   373.8 2194.12
   390.5 2199.65   400.7 2202.44   423.7 2211.48   433.7 2216.23   447.2 2220.92
#Mann= 3 ,-1 , 0
       0      .1       0  160.96    .045       0  176.48      .1       0
Bank Sta=160.96,176.48
XS Rating Curve= 0 ,0
Exp/Cntr=0.3,0.1

Type RM Length L Ch R = 1 ,2769    ,145.8,152.7,151.4
XS GIS Cut Line= 3
2129529.81510478364824.9193232062129344.05104062  364855.3011522
2129153.07898164364893.495629609
#Sta/Elev= 30
       0 2222.06     3.7 2221.85       7 2220.16    10.3  2217.7    13.7 2215.99
    36.9 2205.93    56.9 2197.69    90.1  2182.6    96.8  2179.3   110.1 2171.87
   113.4 2170.37   116.7 2169.28  122.732167.858     130 2165.84  142.752167.984
   146.6 2168.89     150  2169.2   159.9 2168.29   189.9 2168.29   196.6 2168.64
   199.9 2169.24   209.9 2172.46     220 2174.97   266.8 2181.99   296.9 2186.16
     317 2190.39   330.4 2192.58   340.4 2193.36   360.5 2194.09     383 2196.88
#Mann= 4 ,-1 , 0
       0      .1       0   94.94      .1       0  122.73    .045       0
  142.75      .1       0
Bank Sta=122.73,142.75
XS Rating Curve= 0 ,0
Exp/Cntr=0.3,0.1

Type RM Length L Ch R = 1 ,2617    ,154.3,176.2,168.7
XS GIS Cut Line= 2
2129525.47456229364732.905399621 2129206.0303193364694.710922197
#Sta/Elev= 30
       0  2209.3     2.6 2208.61     9.2 2205.48    19.1 2202.14    45.5 2194.51
    48.9 2193.82    62.1 2188.66    68.7 2185.22    75.3 2181.38    85.2 2174.28
    91.8 2168.73    95.1 2167.33   118.2 2166.42   134.8 2166.92  136.492166.508
   141.4 2165.35     148 2164.58  155.582166.082   161.2 2166.84   204.2 2167.99
   217.2 2168.89     224 2169.63   250.4 2172.93   263.6 2175.15   280.1 2177.33
   293.4 2178.77   303.3 2179.28   306.6 2180.07   314.6 2183.65   321.7 2185.15
#Mann= 4 ,-1 , 0
       0      .1       0   31.79      .1       0  136.49    .045       0
  155.58      .1       0
Bank Sta=136.49,155.58
XS Rating Curve= 0 ,0
Exp/Cntr=0.3,0.1

Type RM Length L Ch R = 1 ,2441    ,162,160.6,152
XS GIS Cut Line= 3
2129548.91217947364630.4748301952129395.26648939364567.974955201
2129221.65528804364541.933340609
#Sta/Elev= 30
       0 2194.54     3.8 2194.16    21.4  2187.3    41.6 2181.42    48.6 2179.64
    57.3 2177.81    63.5 2176.92    81.2 2175.38   109.5 2171.97   113.1 2170.89
   123.7 2166.41   127.3 2165.65   136.62164.859   148.5 2164.02   155.6 2164.76
  161.532164.638   166.2 2164.66   172.8 2165.32   189.4 2164.88   208.1 2165.05
   219.3 2165.42     260 2170.62   272.4 2171.81   292.3 2174.28   305.5 2174.64
   308.9 2175.04   312.2  2176.2   318.8  2179.9   325.4 2182.89   341.4 2189.03
#Mann= 4 ,-1 , 0
       0      .1       0    3.28      .1       0   136.6    .045       0
  161.53      .1       0
Bank Sta=136.6,161.53
XS Rating Curve= 0 ,0
Exp/Cntr=0.3,0.1

Type RM Length L Ch R = 1 ,2280    ,147.4,152.1,148.7
XS GIS Cut Line= 3
2129554.98861086364408.2525056152129396.13459787364432.558231279
2129211.23864222364459.467954367
#Sta/Elev= 30
       0 2194.36    12.6 2190.57    22.5 2187.21    32.5 2183.57    49.1 2176.82
      66 2170.92      73 2169.22    85.6 2166.81    94.8 2164.42  104.952162.953
   108.8  2162.3   115.4 2162.85   121.4 2162.94     138 2162.91   151.9 2163.92
   161.9 2163.03   184.2 2163.24   201.7 2164.31     205 2164.64   211.6 2166.77
   218.3 2167.95   224.9 2168.51   246.1 2169.55     268 2172.27   281.3 2176.16
   291.3 2179.64   314.4 2188.63   329.9 2194.27   337.6 2196.47   347.5 2198.52
#Mann= 3 ,-1 , 0
       0      .1       0  104.95    .045       0   121.4      .1       0
Bank Sta=104.95,121.4
XS Rating Curve= 0 ,0
Exp/Cntr=0.3,0.1

Type RM Length L Ch R = 1 ,2128    ,107.7,111.5,106.8
XS GIS Cut Line= 3
2129523.73867339364291.9331844452129365.75244078364304.086047277
2129183.46081063364334.467876285
#Sta/Elev= 30
       0 2209.92     7.4 2206.01    17.3 2201.27    23.9 2198.34    54.6 2183.18
    63.8 2178.98    72.9 2174.43    79.8 2172.16    86.4 2169.12    96.3 2163.39
    99.6 2162.25   102.8 2161.62  119.65 2160.99   125.9 2160.64   129.2 2159.87
   132.5 2159.69   135.8 2160.67  138.772161.078   172.1 2160.33   192.7 2161.99
     202  2162.9   209.8 2164.01   218.7 2164.66   225.3  2166.3   268.6 2172.25
   275.2 2173.91   281.9 2175.18   298.5 2179.79   315.3 2185.78   343.3 2196.88
#Mann= 3 ,-1 , 0
       0      .1       0  119.65    .045       0  138.77      .1       0
Bank Sta=119.65,138.77
XS Rating Curve= 0 ,0
Exp/Cntr=0.3,0.1

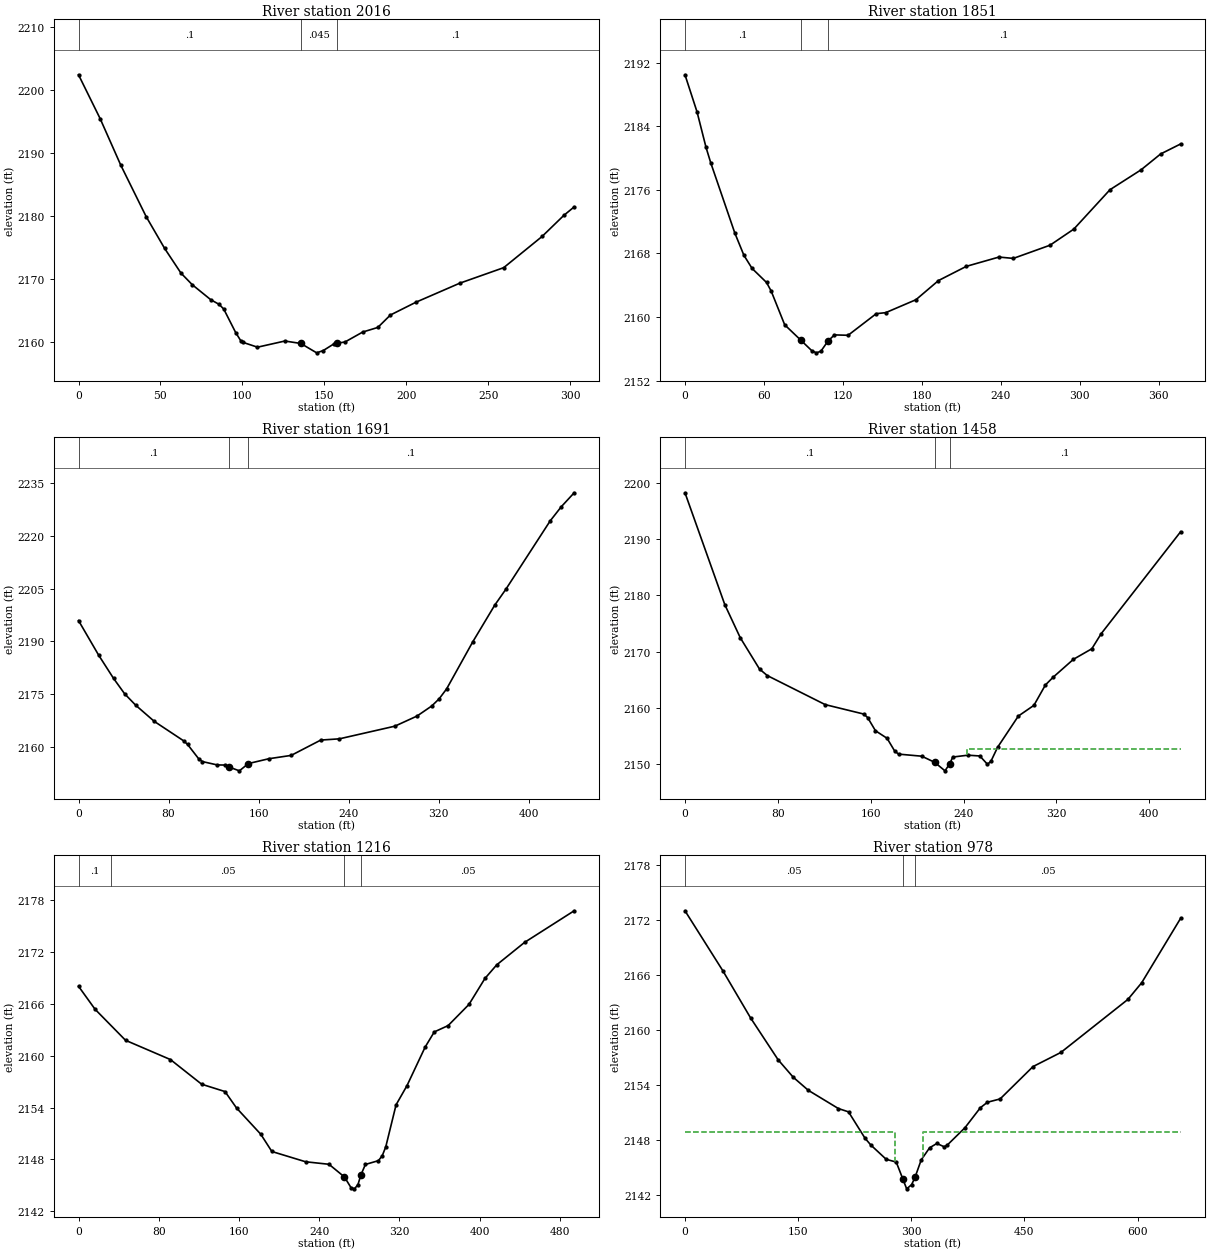
Type RM Length L Ch R = 1 ,2016    ,164.1,165.4,159.9
XS GIS Cut Line= 2
 2129479.3289853364198.9238560352129182.10681072364254.479519203
#Sta/Elev= 30
       0 2202.46    13.2 2195.48    25.8 2188.07    41.3 2179.88    52.5 2174.85
    62.5 2170.91    69.4 2169.06    80.7 2166.67    85.8 2165.93    88.6 2165.19
    95.9 2161.44    99.2 2160.06   100.3 2159.89   109.2 2159.12   125.9  2160.1
  135.612159.712   145.3 2158.22   149.3 2158.58   155.9 2159.66  157.932159.752
   162.6 2159.95   173.4 2161.53   182.6 2162.26   190.3 2164.24     206 2166.29
   232.5 2169.29   259.4 2171.77   282.8 2176.73   296.1 2180.09   302.4 2181.44
#Mann= 3 ,-1 , 0
       0      .1       0  135.61    .045       0  157.93      .1       0
Bank Sta=135.61,157.93
XS Rating Curve= 0 ,0
Exp/Cntr=0.3,0.1

Type RM Length L Ch R = 1 ,1851    ,149.2,160.2,155.2
XS GIS Cut Line= 3
2129417.99544653364043.0350601972129286.32904321364084.701643527
2129062.44005528 364167.47936511
#Sta/Elev= 30
       0  2190.5     9.2 2185.81      16 2181.36    19.6 2179.41    37.9 2170.57
    44.8 2167.77      51 2166.12      62 2164.35    65.5 2163.28    75.8 2159.02
   88.162157.069    96.4 2155.76    99.9 2155.49   103.3 2155.69  108.672156.962
   113.6 2157.75     124  2157.7   145.4 2160.42   152.6 2160.55   175.6 2162.18
   192.7 2164.59   213.9 2166.38   238.7 2167.55   249.6 2167.38   277.5 2169.04
   295.6 2171.07   323.1 2176.03   346.7 2178.53   361.6 2180.53   376.8 2181.79
#Mann= 3 ,-1 , 0
       0      .1       0   88.16    .045       0  108.67      .1       0
Bank Sta=88.16,108.67
XS Rating Curve= 0 ,0
Exp/Cntr=0.3,0.1

Type RM Length L Ch R = 1 ,1691    ,231.7,233.1,228
XS GIS Cut Line= 2
2129406.32880321363946.9240319432128966.88447213363974.701863527
#Sta/Elev= 30
       0  2195.9      18    2186    31.1 2179.46      41 2175.06    50.9 2171.79
    67.3 2167.23    93.6 2161.65    96.9 2160.66   106.7 2156.61     110  2155.8
   123.2 2154.84   129.8 2154.81  133.732154.245   142.9 2153.16  150.882155.231
   169.2 2156.61   188.9 2157.55   215.2 2161.91   231.7 2162.26     281 2165.86
   300.7 2168.74   313.8 2171.61   320.4 2173.66     327 2176.47   350.1 2189.78
   369.7 2200.26   379.6 2204.79     419 2224.25   428.9 2228.29   440.3 2232.24
#Mann= 3 ,-1 , 0
       0      .1       0  133.73    .045       0  150.88      .1       0
Bank Sta=133.73,150.88
XS Rating Curve= 0 ,0
Exp/Cntr=0.3,0.1

Type RM Length L Ch R = 1 ,1458    ,241.4,242.1,236.7
XS GIS Cut Line= 2
2129412.30123222363711.646287277 2128991.4677563363783.868255705
#Sta/Elev= 30
       0 2198.19    34.3 2178.33    47.6 2172.46    64.2 2166.89    70.9 2165.73
   120.8 2160.57   154.1 2158.89   157.4 2158.26   164.1 2155.93   174.1 2154.59
   180.7 2152.31     184 2151.78     204 2151.41  215.122150.323     224 2148.81
  228.162150.098   230.7 2151.26   243.7 2151.59     254 2151.45   260.6 2149.97
   263.6 2150.52   269.3 2152.99   287.2 2158.54   300.6 2160.44   310.5 2164.06
   317.2 2165.44   334.6 2168.61   350.5 2170.49   358.5 2173.15     427 2191.27
#Mann= 3 ,-1 , 0
       0      .1       0  215.12    .045       0  228.16      .1       0
#XS Ineff= 2 , 0
                          242.69         2152.66
Permanent Ineff=
       F       F
Bank Sta=215.12,228.16
XS Rating Curve= 0 ,0
Exp/Cntr=0.3,0.1

Type RM Length L Ch R = 1 ,1216    ,236,238.1,228.6
XS GIS Cut Line= 2
2129344.24559405363464.4240127062128875.49554729 363621.36825262
#Sta/Elev= 30
       0 2168.03    16.5 2165.37    46.9 2161.78    91.7 2159.55   122.8  2156.7
   146.1 2155.85   157.6 2153.95   181.8 2150.91   192.8 2148.92   226.5 2147.73
   249.8 2147.44  265.172145.976   271.8 2144.73   275.2  2144.6   278.7 2145.09
  281.542146.184   286.1 2147.42   299.1 2147.86   302.9 2148.43   306.4 2149.45
   316.7 2154.32   327.6 2156.54   345.7    2161   354.8 2162.75   368.6 2163.48
   389.4 2165.93   405.3 2168.93   417.1 2170.51   444.8  2173.1   494.3 2176.76
#Mann= 4 ,-1 , 0
       0      .1       0    32.2     .05       0  265.17    .045       0
  281.54     .05       0
Bank Sta=265.17,281.54
XS Rating Curve= 0 ,0
Exp/Cntr=0.5,0.3

Type RM Length L Ch R = 1 ,978     ,52.6,52.5,52.3
XS GIS Cut Line= 4
2129349.34630564363316.8462238612129097.05448738363360.526910782
2128823.16559947363419.4159006182128704.55461621363442.887966529
#Sta/Elev= 30
       0 2172.99    50.3 2166.43    86.9 2161.31   123.5 2156.73   143.5 2154.83
   163.5  2153.4   203.4 2151.41   216.8 2151.05   238.7 2148.17   246.5 2147.42
   266.8 2145.87   280.1 2145.57  288.622143.765   293.9 2142.65   300.4  2143.1
  304.912143.889   313.2 2145.81   324.3 2147.13   333.9  2147.6   343.6 2147.24
   347.3 2147.39   371.2 2149.32   391.6  2151.5     401  2152.1   417.8 2152.46
   461.4 2155.99   498.3 2157.53   587.2 2163.32   605.5 2165.14   657.1 2172.17
#Mann= 3 ,-1 , 0
       0     .05       0  288.62    .045       0  304.91     .05       0
#XS Ineff= 2 , 0
           278.6  2148.8   314.9          2148.8
Permanent Ineff=
       F       F
Bank Sta=288.62,304.91
XS Rating Curve= 0 ,0
Exp/Cntr=0.5,0.3

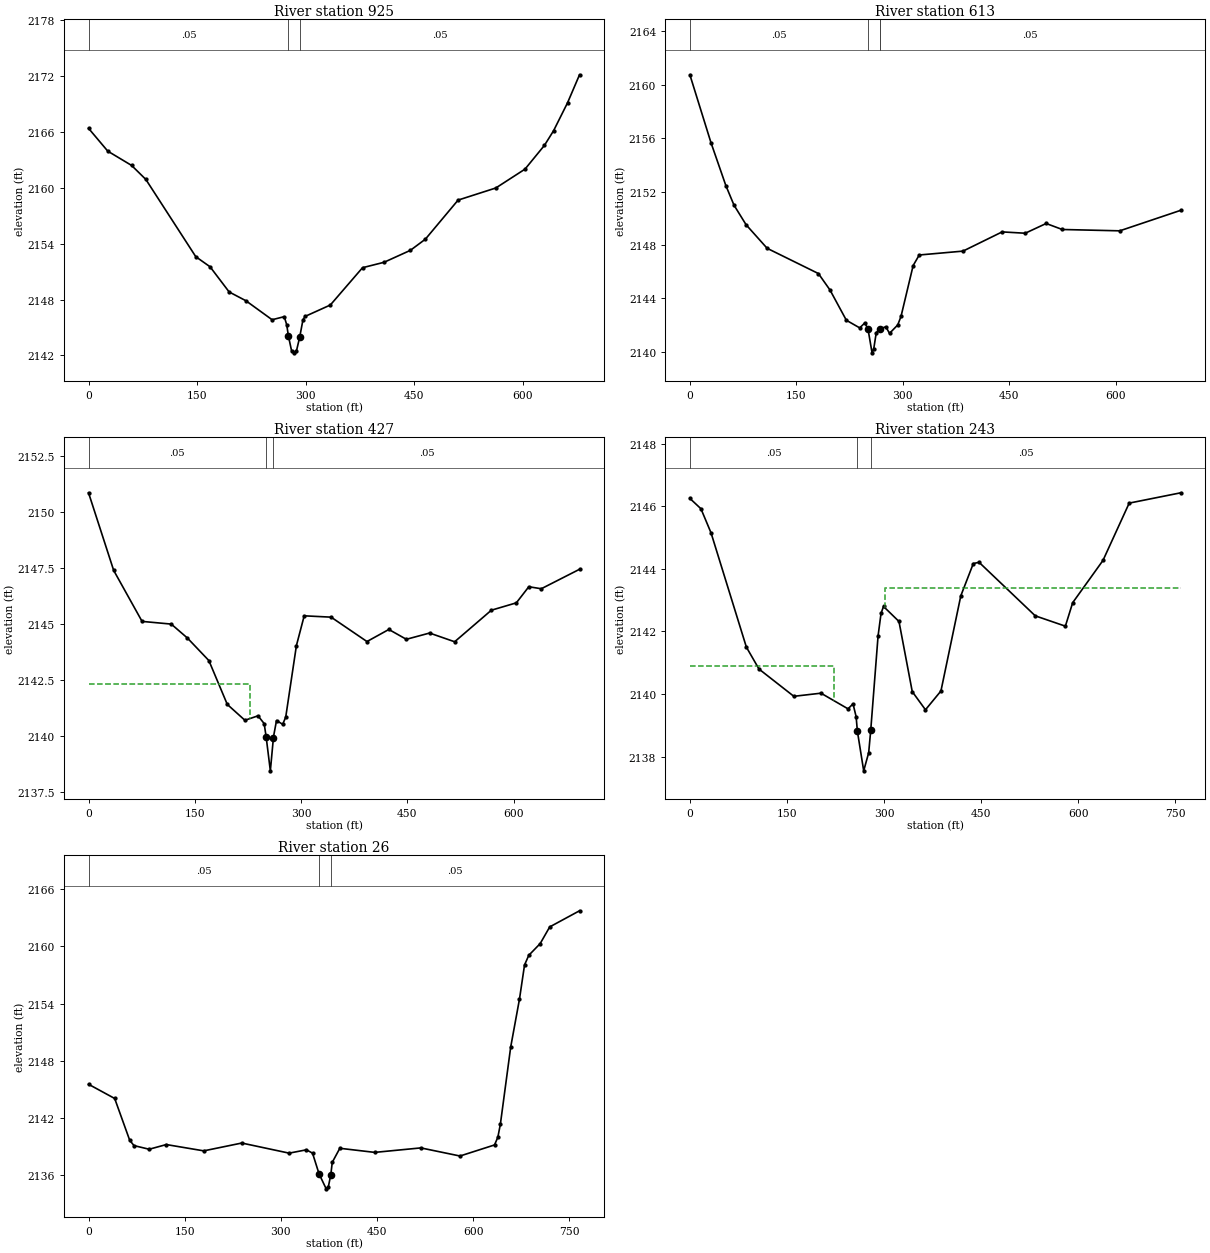
Type RM Length L Ch R = 1 ,925     ,298.1,311.6,308.7
XS GIS Cut Line= 4
2129329.55467853363289.7629446982129082.71429297 363309.63560836
2129013.26987803363325.7467966082128661.86933413363403.501562372
#Sta/Elev= 30
       0 2166.36    26.6 2163.91    59.5 2162.38    79.2 2160.88   148.3 2152.59
     168 2151.51   194.4 2148.81   217.5 2147.87   253.8 2145.83   270.6 2146.16
     274 2145.29  276.362144.071   280.8 2142.47   284.1 2142.28   287.5  2142.5
  291.972143.975   296.4  2145.8   299.2 2146.18   334.3 2147.41   378.8 2151.41
   408.5 2151.99   444.9 2153.27   465.7 2154.47   510.9 2158.66   563.1 2159.96
   603.4 2161.98   630.3 2164.53     643 2166.11   662.2 2169.09   678.8  2172.1
#Mann= 3 , 0 , 0
       0     .05       0  276.36    .045       0  291.97     .05       0
Bank Sta=276.36,291.97
XS Rating Curve= 0 ,0
Exp/Cntr=0.5,0.3

Type RM Length L Ch R = 1 ,613     ,180.9,186,185.6
XS GIS Cut Line= 3
2129344.24559405363241.5071357042129084.52334446363024.146021858
2128748.41214004362915.812905192
#Sta/Elev= 30
       0 2160.75    29.7 2155.67    50.7 2152.45    62.2 2150.98    79.3 2149.51
   108.9 2147.75   181.1 2145.86   197.4 2144.63   220.5 2142.36   239.3 2141.79
   246.5 2142.16     251  2141.7   256.7 2139.92     259  2140.2   262.6 2141.42
   267.3 2141.73   267.6 2141.72   276.1 2141.87   281.3 2141.38   292.9 2142.01
   297.5 2142.65   314.6 2146.46   323.2 2147.25   384.8 2147.54     440 2148.98
   472.5 2148.88     502 2149.61   524.7 2149.16   605.7 2149.06   691.8  2150.6
#Mann= 4 ,-1 , 0
       0     .05       0     251    .045       0   267.3    .045       0
   267.6     .05       0
Bank Sta=251,267.3
XS Rating Curve= 0 ,0
Exp/Cntr=0.3,0.1

Type RM Length L Ch R = 1 ,427     ,182.3,184.6,182.6
XS GIS Cut Line= 3
2129401.79764429363113.2085077762129197.80461395362877.965539947
2128842.76989096362737.340493113
#Sta/Elev= 30
       0 2150.86    35.5 2147.39    75.6 2145.11   116.8 2144.99   139.5 2144.37
   169.9 2143.36   195.9  2141.4   220.8 2140.69   239.3 2140.89     248 2140.54
   250.8 2139.94   256.7 2138.43     261  2139.9     261 2139.93   265.4 2140.68
   274.1 2140.51   278.4 2140.83   293.5 2144.03   304.5 2145.36   342.5  2145.3
   393.1 2144.21     424 2144.75   448.7 2144.31   481.5 2144.59   516.9  2144.2
   568.7 2145.61     604 2145.94   621.6 2146.66   639.2 2146.57   693.2 2147.44
#Mann= 3 , 0 , 0
       0     .05       0   250.8    .045       0     261     .05       0
#XS Ineff= 2 , 0
          227.53  2142.3
Permanent Ineff=
       F       F
Bank Sta=250.8,261
XS Rating Curve= 0 ,0
Exp/Cntr=0.3,0.1

Type RM Length L Ch R = 1 ,243     ,211,217,201.6
XS GIS Cut Line= 6
2129547.28390187 363022.236576872129470.89494705362903.486486286
2129400.75597972362843.0696123692129358.39484397362797.236370698
2129216.72813255362756.9585641182128910.47808889362683.347490862
#Sta/Elev= 30
       0 2146.25    17.1 2145.92    32.7 2145.15    87.3  2141.5   106.8  2140.8
   160.6 2139.93   202.5 2140.03   244.3 2139.53     252 2139.69   256.8 2139.28
  258.732138.818   268.5 2137.55   276.2 2138.13  279.342138.841   290.7 2141.86
   295.3 2142.58   299.1  2142.8     323 2142.32   343.5 2140.08   363.9  2139.5
   387.8  2140.1   418.5 2143.14   437.8 2144.17   446.7 2144.21   533.5  2142.5
     580 2142.17   591.3 2142.92   638.1 2144.27   678.6  2146.1   758.4 2146.43
#Mann= 3 ,-1 , 0
       0     .05       0  258.73    .045       0  279.34     .05       0
#XS Ineff= 2 , 0
           223.2  2140.9  301.98          2143.4
Permanent Ineff=
       F       F
Bank Sta=258.73,279.34
XS Rating Curve= 0 ,0
Exp/Cntr=0.3,0.1

Type RM Length L Ch R = 1 ,26      ,22.87,25.75,28.63
XS GIS Cut Line= 4
2129584.78382689363031.2641178672129512.56153038 362705.56988737
2129458.39497206362669.4587391172129122.97832003362519.458711028
#Sta/Elev= 30
       0 2145.55    40.8 2144.06    64.3 2139.67      71 2139.12    94.6 2138.74
   121.4 2139.23   179.8 2138.57   239.1 2139.39     313 2138.33     340 2138.68
   349.5 2138.33  359.652136.168   370.8 2134.59   374.2 2134.81  378.04 2136.08
   380.3 2137.37   392.1 2138.84   446.6 2138.41   518.5 2138.88   579.6 2138.03
   633.5 2139.19   638.7 2140.01   642.6 2141.36   658.7 2149.45   672.4 2154.47
   680.3 2158.05   686.9 2159.06   704.7 2160.29   719.6 2162.04   766.1 2163.73
#Mann= 3 ,-1 , 0
       0     .05       0  359.65    .045       0  378.04     .05       0
Bank Sta=359.65,378.04
XS Rating Curve= 0 ,0
Exp/Cntr=0.3,0.1
LCMann Table=0

Chan Stop Cuts=-1
Use User Specified Reach Order=0
Composite Channel Slope=5